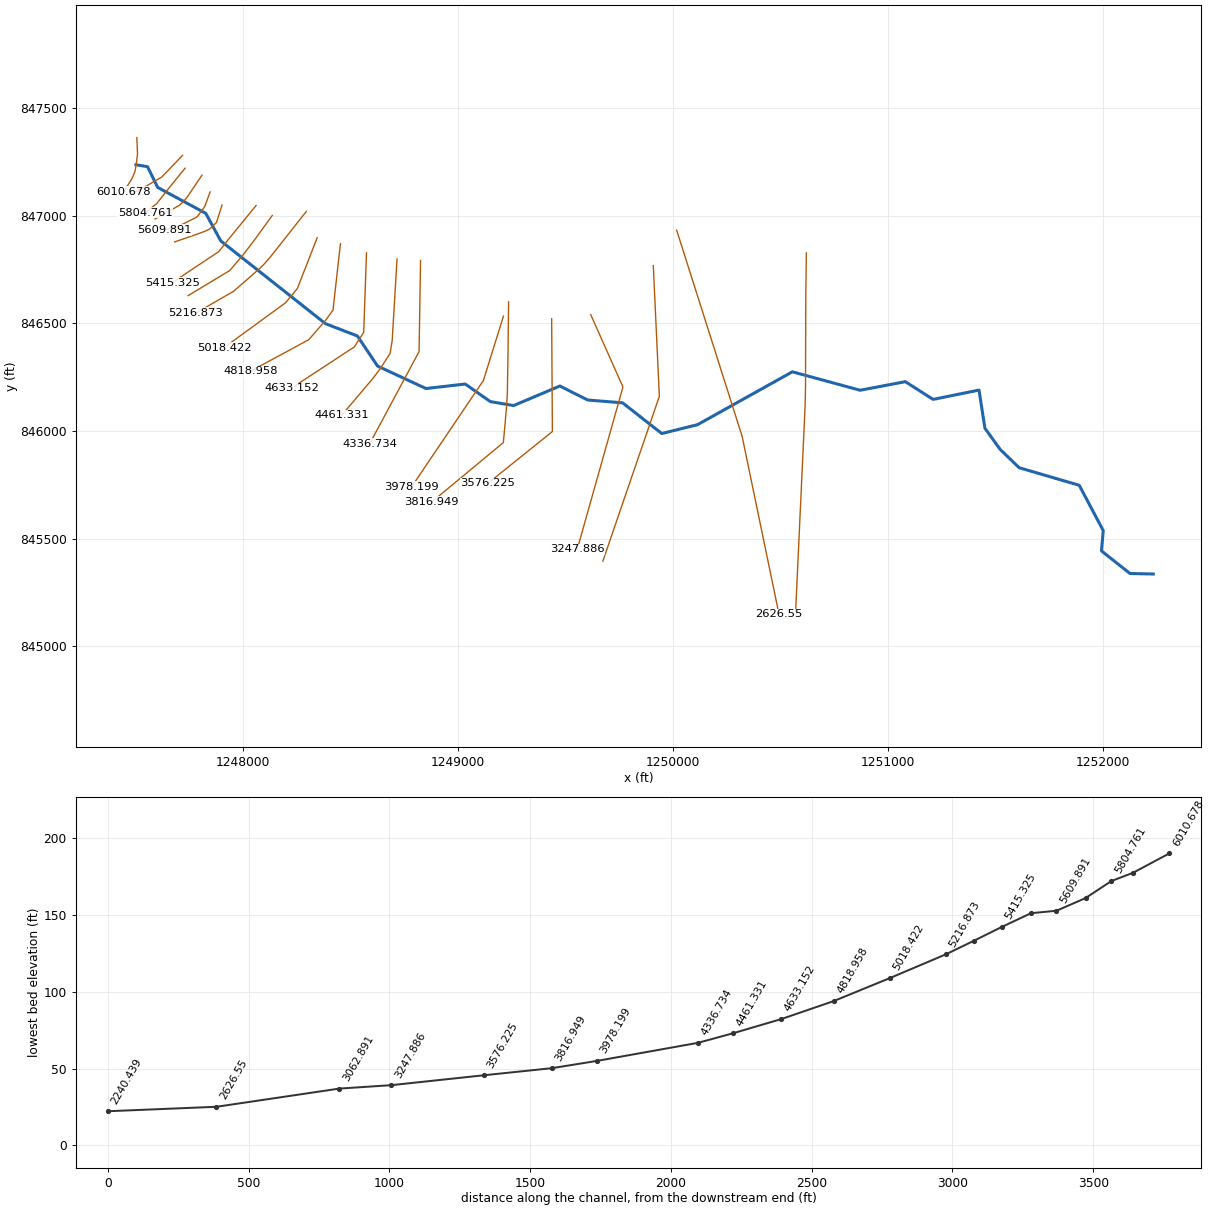
--- 127_ras.prj (project) ---

Proj Title=127
Current Plan=p01
Default Exp/Contr=0.3,0.1
English Units
Geom File=g01
Flow File=f01
Plan File=p01
Y Axis Title=Elevation
X Axis Title(PF)=Main Channel Distance
X Axis Title(XS)=Station
BEGIN DESCRIPTION:
RFD model 127 exported to HEC-RAS
END DESCRIPTION:

--- 127_ras.p01 (plan) ---

Plan Title=Plan 01
Program Version=4.10
Short Identifier=Plan 01
Geom File=g01
Flow File=f01
Subcritical Flow
Calc Critical at every XS
Secant Critical Depth

--- 127_ras.f01 (steady flow) ---

Flow Title=Flow 01
Program Version=5.01
Number of Profiles= 5
Profile Names=10yr,25yr,50yr,100yr,500yr
River Rch & RM=127,21,6010.678
  107.43  190.48  270.16  365.07  641.85
River Rch & RM=127,21,5880.971
  192.84  346.34  497.29  680.94 1240.52
River Rch & RM=127,21,5713.002
  196.52   353.1   507.2  694.81 1267.24
River Rch & RM=127,21,5609.891
  205.72     370  531.99  729.53 1334.26
River Rch & RM=127,21, 5519.52
  213.08  383.52  551.83  757.34 1388.08
River Rch & RM=127,21,5415.325
  221.03  398.16  573.33  787.51 1446.59
River Rch & RM=127,21,5316.099
  226.53  408.29  588.23  808.41 1487.22
River Rch & RM=127,21,5216.873
  230.81  416.17  599.82  824.69 1518.88
River Rch & RM=127,21,5018.422
  239.36  431.93     623  857.27 1582.38
River Rch & RM=127,21,4818.958
   241.8  436.43  629.63  866.59 1600.57
River Rch & RM=127,21,4633.152
  264.95  479.17  692.62  955.26 1774.17
River Rch & RM=127,21,4461.331
  271.64  491.54  710.87  980.99 1824.71
River Rch & RM=127,21,4336.734
  274.68  497.16  719.17  992.69 1847.72
River Rch & RM=127,21,3978.199
  404.55  738.46 1076.94 1499.63 2857.73
River Rch & RM=127,21,3816.949
  405.75   740.7 1080.28 1504.38  2867.3
River Rch & RM=127,21,3576.225
  421.36  769.84 1123.66 1566.13 2991.85
River Rch & RM=127,21,3247.886
  425.56  777.68 1135.35 1582.77 3025.46
River Rch & RM=127,21,3062.891
  433.95  793.37 1158.72 1616.07 3092.78
River Rch & RM=127,21, 2626.55
  440.55  805.69 1177.09 1642.25 3145.76
River Rch & RM=127,21,2240.439
  780.78 1445.95 2138.04 3021.86  5993.2
Boundary for River Rch & Prof#=127,21,1
Up Type= 0
Dn Type= 2
Boundary for River Rch & Prof#=127,21,2
Up Type= 0
Dn Type= 2
Boundary for River Rch & Prof#=127,21,2
Up Type= 0
Dn Type= 2
Boundary for River Rch & Prof#=127,21,2
Up Type= 0
Dn Type= 2
Boundary for River Rch & Prof#=127,21,2
Up Type= 0
Dn Type= 2

--- 127_ras.g01 (geometry) ---

Geom Title=127
Program Version=4.10

River Reach=127,21
Reach XY= 30
1247504.80863797 847237.666064091247558.51806569847228.714491196
1247605.51381235  847132.48509821247829.17793838847011.924492236
1247899.17791406846883.5911947521248385.57769336846499.073646664
1248534.01519336846441.7819799971248627.76519336846302.025035553
1248852.70901277846197.6251452251249035.20895979846218.458467072
1249151.87558981846136.7918210831249260.20889079846118.458489995
1249475.20883032 846209.291790211249604.37545716 846144.29180562
1249766.87540905 846130.958471461249948.54201818845988.458508224
1250114.93175394  846029.51927691250555.76496505846275.352524714
1250870.76487003846189.5192075061251080.76480953846229.519189524
1251209.93143585846147.0192101031251423.26470781846190.352524387
1251450.76469452846012.8525759971251521.59800417845914.519269648
1251609.93130907845829.5192921821251889.09789136845747.852641444
1252000.76451904845537.0193671221251992.43118539845442.852728545
 1252124.9311434845337.8527556561252233.26444485845335.352753206

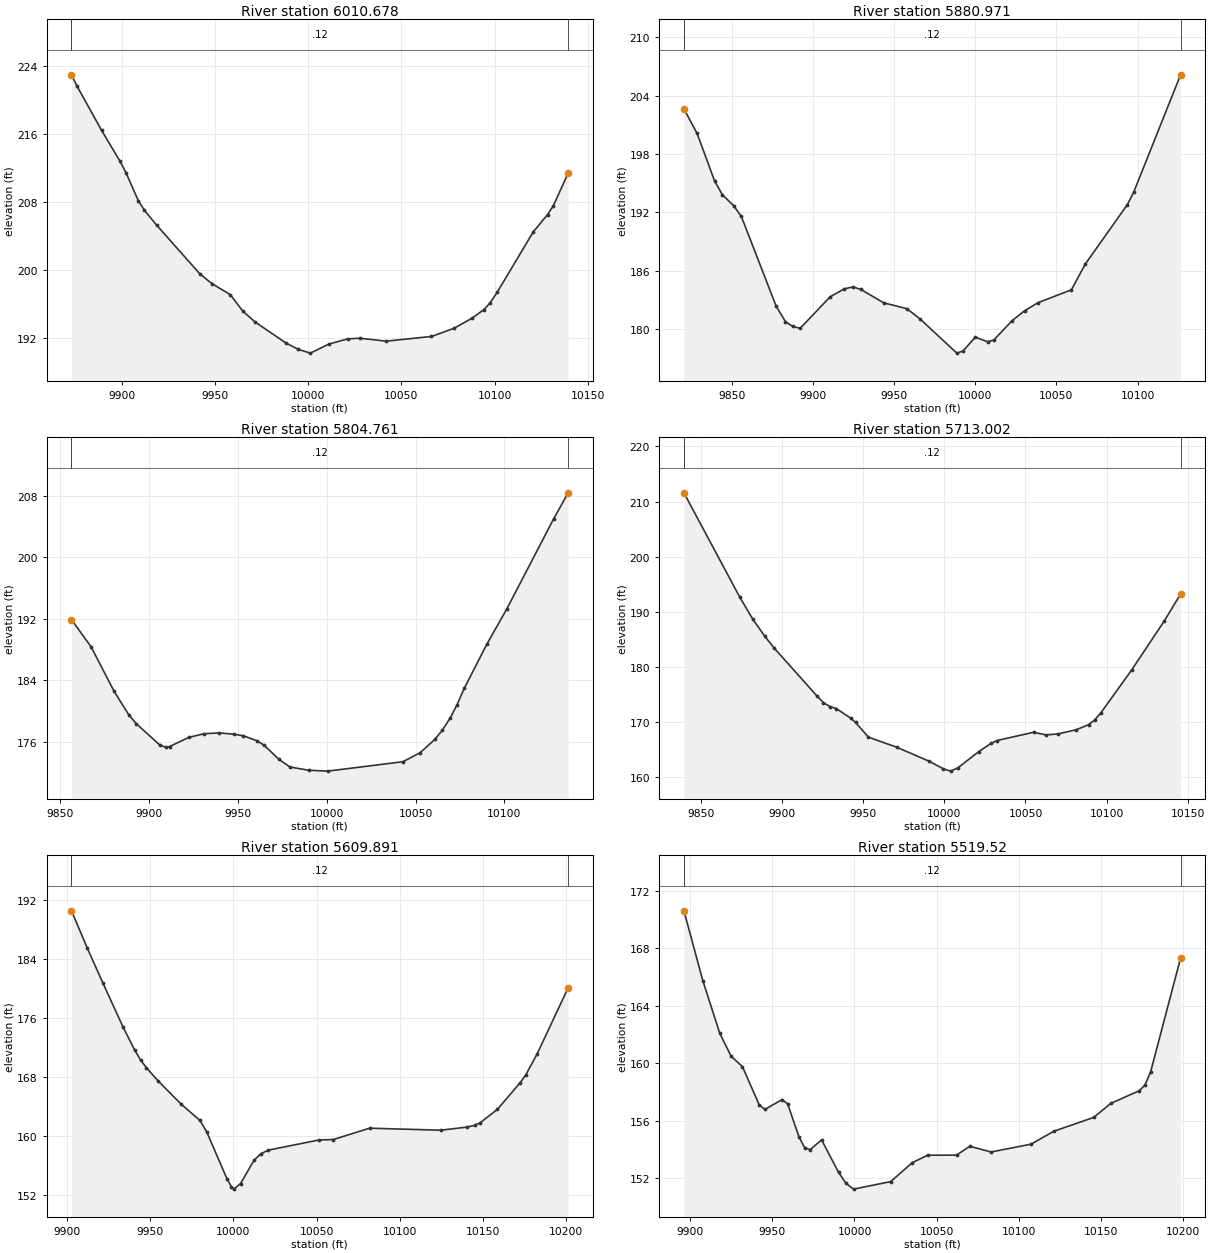
Type RM Length L Ch R = 1 ,6010.678,129.707100,129.707100,129.707100
XS GIS Cut Line= 6
1247508.82711466847364.1199429611247512.08232299847287.080012405
 1247505.7139954847236.579635111 1247500.2392277847206.674589252
1247486.98238187847174.5384540361247448.35126724847112.188488469
#Sta/Elev= 30
 9872.99222.92229876.032221.55869889.167216.38599899.018212.76859902.302211.3844
9908.869208.11759912.153206.9906 9918.72205.24169941.707199.56459948.274198.3823
9958.183  197.099964.798195.17339971.413193.8846 9987.95191.41439994.565190.6603
10001.17190.207110011.18191.278110021.19191.880410027.86191.958510041.83191.6136
10066.17192.166110078.29193.1283   10088194.323210094.23195.311610097.59196.1024
10101.45197.364710120.75204.448510128.46206.4979 10131.6207.545210139.51211.3728
#Mann= 3 , 0 , 0
 9872.99    0.12       0 9872.99    0.12       010139.51    0.12       0
#XS Ineff= 2 , 0
       0                10048.82       0
Bank Sta=9872.99,10139.51
Exp/Cntr=0.3,0.1

Type RM Length L Ch R = 1 ,5880.971,76.210400,76.210400,76.210400
XS GIS Cut Line= 4
1247721.50072577847281.6546651831247624.92954521 847180.74320685
1247557.65523966 847141.680706851247479.53023966847099.362998516
#Sta/Elev= 30
9820.253202.65059828.385200.1236 9839.17195.23529843.915193.83319851.091192.6574
9855.632191.59719877.132182.34949882.879 180.755 9887.42180.25819891.961 180.071
9910.348183.30089919.208184.13929924.584184.32679929.329184.07319943.565182.6879
9957.801182.08699965.815181.04659988.577177.51599992.371177.73049999.959179.1603
10007.55178.686810011.34178.859710022.72180.866510030.31181.867910038.59182.7038
10059.26184.032610067.74186.6662 10093.7192.790210097.59 194.04910126.57206.1577
#Mann= 3 , 0 , 0
9820.253    0.12       09820.253    0.12       010126.57    0.12       0
#XS Ineff= 2 , 0
       09927.037         10040.3       0
Bank Sta=9820.253,10126.57
Exp/Cntr=0.3,0.1

Type RM Length L Ch R = 1 ,5804.761,91.759400,91.759400,91.759400
XS GIS Cut Line= 4
1247733.43648966847221.975845739 1247666.1621841847139.510567961
1247601.05801743847057.0452901831247547.88961466 847014.72758185
#Sta/Elev= 30
9856.446191.91149867.458 188.3739880.449182.56859888.628179.53749892.862178.3689
  9906.4175.53139909.799175.2999 9911.59175.38949922.501176.58259930.969177.0587
9939.437177.16379947.921 176.9959953.111176.78929960.607176.16029964.816175.5664
9973.176173.71879979.388172.72469989.977172.302810000.57172.189910042.92173.4153
 10052.6174.585910060.96176.335310065.14177.532110069.68179.165710073.29180.7893
10077.48182.992510090.06188.673910101.29193.2638 10127.8205.059610135.89208.4124
#Mann= 3 , 0 , 0
9856.446    0.12       09856.446    0.12       010135.89    0.12       0
#XS Ineff= 2 , 0
       09939.159        10028.67       0
Bank Sta=9856.446,10135.89
Exp/Cntr=0.3,0.1

Type RM Length L Ch R = 1 ,5713.002,103.110200,103.110200,103.110200
XS GIS Cut Line= 6
1247811.79095747847189.5134182071247743.26830567847087.978943949
1247729.86855974847071.5408214241247718.65630794 847060.67091904
1247705.84779732847048.5748117591247593.46253132 846985.43070685
#Sta/Elev= 30
9839.683211.57659874.142192.62049882.058  188.679889.576185.52699895.441183.3638
9921.639174.72549925.597173.52849929.555172.82279933.513172.45939942.361170.7135
9945.387169.95099953.304 167.2619970.595165.46129990.408162.93529999.522161.5191
   10004161.106510008.53161.731610021.19164.629910028.72166.117510032.48166.6569
10055.06168.159810062.59167.667310070.12167.8571 10081.4168.625910088.93169.5456
10092.69 170.41510096.46171.6812 10115.4179.448410135.49188.333610145.53193.2213
#Mann= 3 , 0 , 0
9839.683    0.12       09839.683    0.12       010145.53    0.12       0
#XS Ineff= 2 , 0
       09937.968        10043.49       0
Bank Sta=9839.683,10145.53
Exp/Cntr=0.3,0.1

Type RM Length L Ch R = 1 ,5609.891,90.371300,90.371300,90.371300
XS GIS Cut Line= 5
1247849.53892021847111.2987624051247824.58232299 847044.02445685
1247788.77503132 846995.196331851247711.73510077 846956.13383185
1247634.69517021846934.432442961
#Sta/Elev= 30
9902.619190.48459912.172 185.4129921.605180.67339933.645174.75759940.643171.6453
9944.143170.31899947.642169.27289954.641167.49259968.638164.32339979.911162.1256
9983.979160.57359996.184154.21289998.817153.166310000.25152.842410004.32153.6021
10012.46156.772310016.53 157.62610021.01158.116410051.45159.490210060.16159.5517
10081.92161.086510124.74160.811810140.32161.229710145.19161.4716 10148.6161.8517
10158.83163.640510172.46167.233710175.87168.305410182.69171.134710201.34180.0794
#Mann= 3 , 0 , 0
9902.619    0.12       09902.619    0.12       010201.34    0.12       0
#XS Ineff= 2 , 0
       09958.641        10082.52       0
Bank Sta=9902.619,10201.34
Exp/Cntr=0.3,0.1

Type RM Length L Ch R = 1 , 5519.52,104.195300,104.195300,104.195300
XS GIS Cut Line= 6
1247904.87746188847050.5348735161247878.83579521846969.154665183
1247846.67442663846938.4703329411247825.51677473846928.640120396
1247788.05237216846914.7040595081247684.60836466846879.093901294
#Sta/Elev= 30
9896.074170.60049907.595 165.7449917.927162.08349924.815160.49349931.702 159.771
9942.034157.09369945.478156.79969955.814157.4774 9959.26157.18319966.152 154.896
9969.598154.14279973.044154.00059979.937154.68469990.327152.41339994.862151.6586
9999.396151.255610022.07151.780310035.22153.095110044.56153.6108 10062.2153.6201
10070.24154.234110083.21153.838510107.57154.380310121.44155.279410145.73 156.238
10156.14157.213710173.49158.095310176.96158.485210180.43159.406910198.68167.3238
#Mann= 3 , 0 , 0
9896.074    0.12       09896.074    0.12       010198.68    0.12       0
#XS Ineff= 2 , 0
       09958.319        10072.62       0
Bank Sta=9896.074,10198.68
Exp/Cntr=0.3,0.1

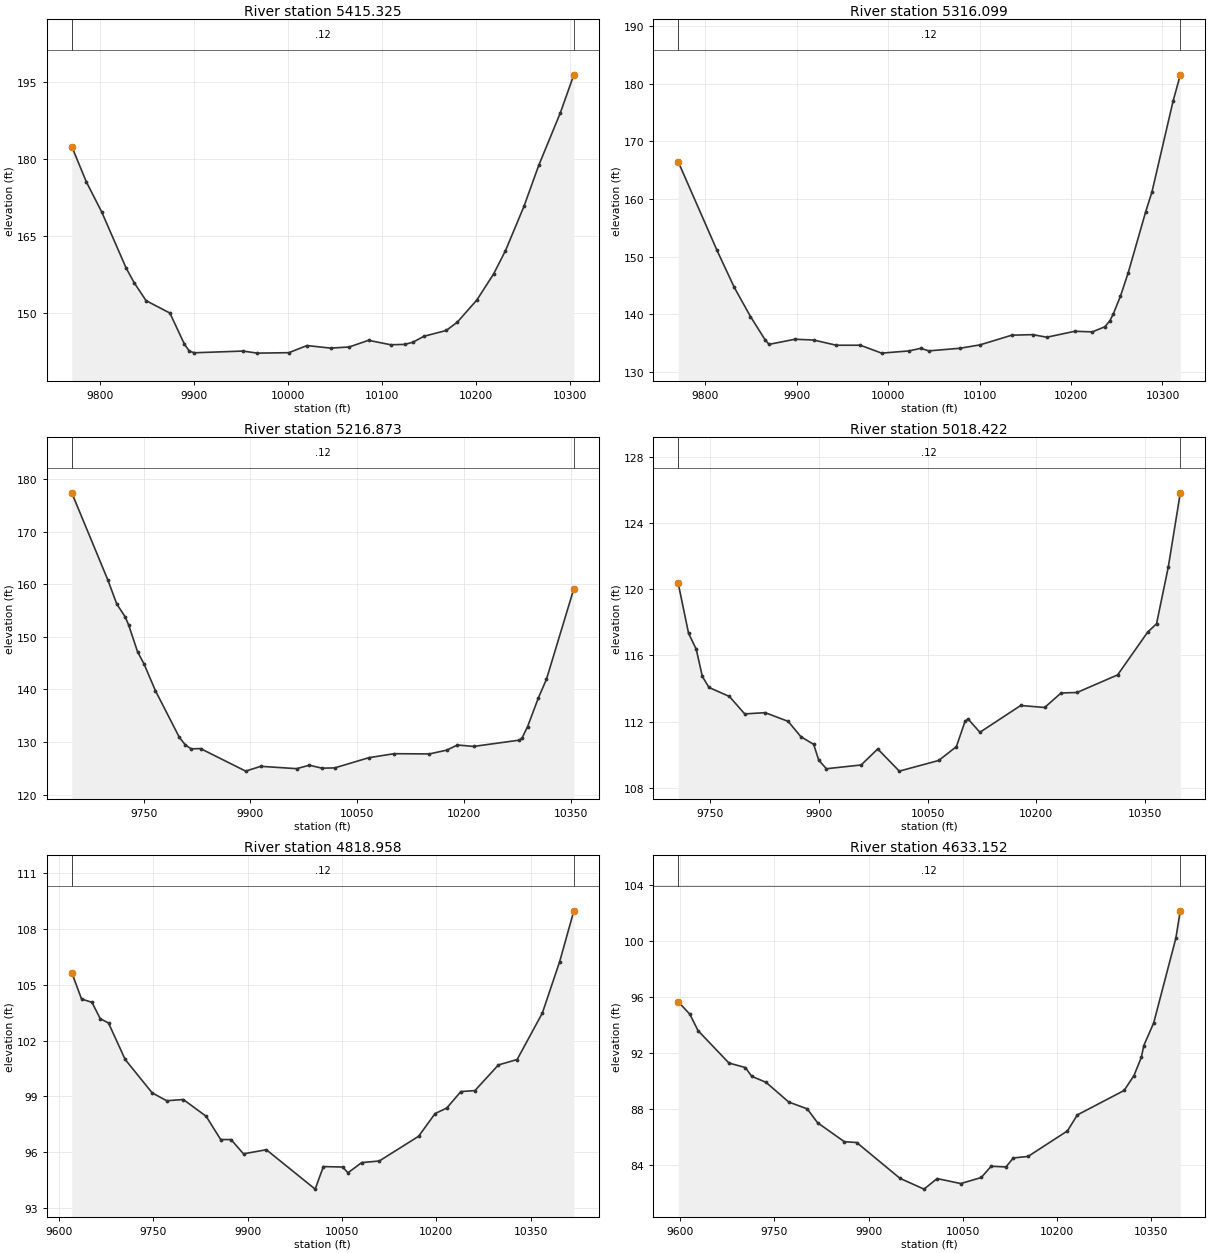
Type RM Length L Ch R = 1 ,5415.325,99.225700,99.225700,99.225700
XS GIS Cut Line= 6
1248063.29760077847048.3647346281247939.27008115846896.604801836
1247918.33705888846870.4718353151247917.13705883846868.871835349
1247889.75097603846834.036554802 1247673.9746841846690.291817961
#Sta/Elev= 30
9769.522182.48159785.132175.57419801.493169.72649827.503158.81859835.977155.9932
9848.688152.49369874.076150.0766 9889.63144.00319894.814142.68189899.999142.3477
9951.844  142.689967.421142.2791 10000.9142.3669 10020.2143.754110045.31143.2555
10065.17143.4764 10085.8144.770510109.45143.906810124.35143.9785 10133.1144.4021
10144.93145.568810168.58146.682710180.41148.309110201.28152.632110219.03157.6666
10231.66162.191510251.37170.813710267.14178.803910290.04188.967710304.58196.4301
#Mann= 3 , 0 , 0
9769.522    0.12       09769.522    0.12       010304.58    0.12       0
#XS Ineff= 2 , 0
       09907.733        10046.82       0
Bank Sta=9769.522,10304.58
Exp/Cntr=0.3,0.1

Type RM Length L Ch R = 1 ,5316.099,99.225600,99.225600,99.225600
XS GIS Cut Line= 6
1248138.16739243847001.7067485161248054.99832714846887.300264205
1248002.29080527846818.2504259271248001.05516212846816.677789285
1247940.90176743846746.2814012941247747.54239243846629.527929072
#Sta/Elev= 30
 9770.69 166.4329813.128151.05069831.992144.63279849.633139.5987 9865.47135.5992
9869.914134.76829898.307135.65479918.701 135.5219943.465134.61499969.648  134.62
9992.994133.246910022.86133.629210035.81134.084610044.44133.637410078.96134.0968
10100.73134.685910135.22136.357410158.21136.454110173.54136.0055 10204.2 137.038
10223.37136.9337 10237.1137.829710242.53138.873910246.36 140.09910254.03143.1203
10262.49147.173210281.53157.708910288.52  161.2310311.51176.917710319.47181.5111
#Mann= 3 , 0 , 0
 9770.69    0.12       0 9770.69    0.12       010319.47    0.12       0
#XS Ineff= 2 , 0
       09909.221        10096.31       0
Bank Sta=9770.69,10319.47
Exp/Cntr=0.3,0.1

Type RM Length L Ch R = 1 ,5216.873,198.451200,198.451200,198.451200
XS GIS Cut Line= 6
1248296.33616094 847020.264497921248128.27286556846807.581713471
1248096.23202325846771.2295588171248073.96075942846750.486128147
 1247959.1309341846649.927234627 1247783.3496841846548.364734627
#Sta/Elev= 30
9649.037177.35149699.713160.79619712.257156.22729724.162153.76069728.984152.2262
9741.528147.1337 9750.62144.81769766.617139.74359800.069130.91879808.432129.4583
9816.795128.68739829.996128.73869893.496 124.4519914.663125.36339965.123124.9208
9982.934125.573310000.74125.011310018.53125.066110066.64127.007410102.11127.7653
10151.68127.720610175.99128.441210191.15 129.41810213.88129.146310278.29130.3463
10282.08130.798310289.66132.906210304.82138.369810316.19141.912110354.69159.1158
#Mann= 3 , 0 , 0
9649.037    0.12       09649.037    0.12       010354.69    0.12       0
#XS Ineff= 2 , 0
       09904.701                       0
Bank Sta=9649.037,10354.69
Exp/Cntr=0.3,0.1

Type RM Length L Ch R = 1 ,5018.422,199.463800,199.463800,199.463800
XS GIS Cut Line= 6
1248347.15176743846898.625151294 1248255.4202579846663.526118555
1248229.83994189 846632.115245621248228.48669127846630.642590617
 1248200.1613958846596.2386161771247914.86010077846388.208484627
#Sta/Elev= 30
9706.129120.35889720.369117.34229730.934116.37719739.394  114.739748.542114.0644
9776.716113.51869797.847112.46429826.021  112.549857.716112.01379875.325111.0866
9892.933110.62249899.977109.66389910.542109.14839958.491109.37799981.275110.3454
10011.04109.003810065.39109.648110089.75110.485210101.93112.033810105.99112.1552
10122.23111.352410178.52112.973910211.56112.8531 10234.2113.729810256.23113.7603
10312.16114.822510353.68117.412810365.86117.9145 10382.1121.353210398.66125.8345
#Mann= 3 , 0 , 0
9706.129    0.12       09706.129    0.12       010398.66    0.12       0
#XS Ineff= 2 , 0
       09896.634                       0
Bank Sta=9706.129,10398.66
Exp/Cntr=0.3,0.1

Type RM Length L Ch R = 1 ,4818.958,185.806600,185.806600,185.806600
XS GIS Cut Line= 6
 1248455.2246841846871.2814012941248420.59381598846561.952949997
1248385.30389696  846513.46533191248384.09285325846511.873674546
1248308.08926743 846424.666817961248035.95385077846277.531401294
#Sta/Elev= 30
9620.545105.6585 9636.09104.23719652.597104.06119665.802103.18279679.007102.9451
9705.418 100.9919748.33599.195829771.44598.771789797.85598.83814 9834.1797.93851
9857.27996.688559873.78696.684799893.59495.919629929.90996.1399310007.5394.02317
10020.5995.2355610051.0595.2101210059.76  94.90210081.5295.4494110109.45 95.5346
10172.0496.8634310198.1498.0814210216.7998.3813810239.1799.2650210261.5599.31694
10298.84100.694810328.68100.987410368.69103.479610396.29106.246310418.82108.9753
#Mann= 3 , 0 , 0
9620.545    0.12       09620.545    0.12       010418.82    0.12       0
#XS Ineff= 2 , 0
       0                               0
Bank Sta=9620.545,10418.82
Exp/Cntr=0.3,0.1

Type RM Length L Ch R = 1 ,4633.152,171.820500,171.820500,171.820500
XS GIS Cut Line= 4
 1248576.3184341846828.3126512941248563.29760077846458.520984627
1248519.93377759846391.1860560591248227.36010077846199.406401293
#Sta/Elev= 30
9596.68395.685739615.10694.799019628.23893.624929677.48191.311149703.74490.98974
9713.592   90.379736.57289.934759772.68488.53096 9802.2388.040689818.64487.05259
9861.32185.698619881.01885.640829949.95983.083799988.31782.3134610009.2483.06881
10046.7982.7096310079.5583.1438410095.2483.9471410118.7883.8944410130.5484.53897
10154.0884.6472410216.8586.4715610232.5487.6079710307.0789.3534910322.7690.41518
10334.5391.7184110338.4692.5625710354.1594.1673710389.45100.208310396.62102.1736
#Mann= 3 , 0 , 0
9596.683    0.12       09596.683    0.12       010396.62    0.12       0
#XS Ineff= 2 , 0
       0                               0
Bank Sta=9596.683,10396.62
Exp/Cntr=0.3,0.1

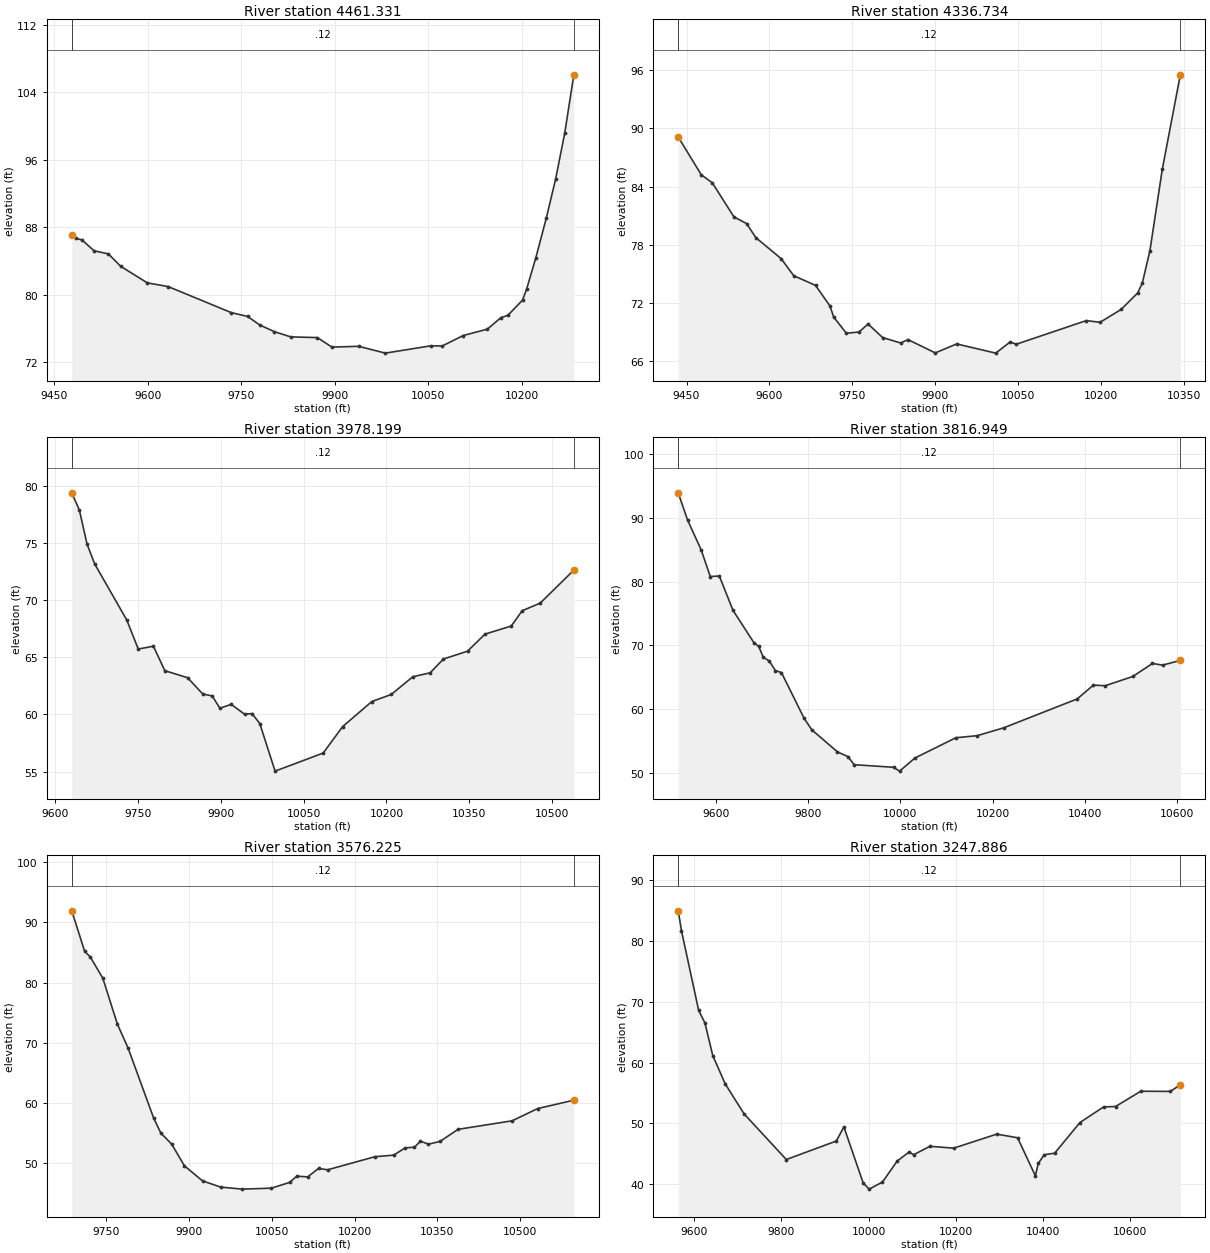
Type RM Length L Ch R = 1 ,4461.331,124.597300,124.597300,124.597300
XS GIS Cut Line= 6
1248718.24551743846799.6668179611248695.67607299846419.458484627
1248685.82205124 846360.721076271248639.73072461846288.840394547
1248602.64133892846240.5128944271248461.23734123846073.438542695
#Sta/Elev= 30
9478.182 87.06189484.36386.650669494.22386.496029513.94385.189869536.94984.81939
9556.66983.348439599.39581.384159632.93480.941069734.14677.853399760.43977.39667
9780.15876.372079803.16575.597949829.45774.977449872.34374.88937 9895.6373.76164
9938.45573.856139981.32673.0472310054.3873.91567 10072.773.8949910106.0975.12994
10145.2275.8956310166.8577.2651610177.8377.5207610201.4979.3303210207.9980.62247
10222.9884.39154 10239.889.1107810254.78 93.755310269.2499.1570510283.85106.0649
#Mann= 3 , 0 , 0
9478.182    0.12       09478.182    0.12       010283.85    0.12       0
#XS Ineff= 2 , 0
       09871.402                       0
Bank Sta=9478.182,10283.85
Exp/Cntr=0.3,0.1

Type RM Length L Ch R = 1 ,4336.734,358.535300,358.535300,358.535300
XS GIS Cut Line= 3
1248827.62051743846792.7223735161248820.67607299846369.111262405
1248591.27792484845941.232211479
#Sta/Elev= 30
9434.98589.109559476.86785.197029496.55584.39368 9535.9380.859189558.89980.17107
9575.30578.732269621.24376.559869644.21274.786179683.58773.794199709.83771.66338
  9716.470.529329739.36968.853769762.33868.976559778.744 69.80689804.99468.41069
9837.80767.846719850.93268.197419900.42466.824889939.23667.7472210009.97 66.7995
10036.0267.9511910047.1967.7171710173.7670.1549110198.9969.9832710237.0471.31282
10266.8373.0016410275.37 74.028110289.1677.39142 10311.585.7665110344.15 95.5294
#Mann= 3 , 0 , 0
9434.985    0.12       09434.985    0.12       010344.15    0.12       0
#XS Ineff= 2 , 0
       09861.461                       0
Bank Sta=9434.985,10344.15
Exp/Cntr=0.3,0.1

Type RM Length L Ch R = 1 ,3978.199,161.249900,161.249900,161.249900
XS GIS Cut Line= 3
1249212.99478361 846534.373699711249119.67881131846234.894533008
1248786.59042487845741.579433709
#Sta/Elev= 30
 9630.3279.407059644.132 77.89249657.87874.932969671.62373.196749730.04268.25264
9750.66165.726849778.15265.972989798.77163.831299840.00863.214379867.49961.78565
9884.68161.620249898.42760.539219919.04560.88313  9943.160.018729956.61960.07535
9970.67459.202829998.38455.0340810085.48 56.617110120.7858.9392610173.5561.12882
10208.73 61.748110247.7863.3013510279.0863.64274 10303.264.8529610346.7565.53734
10378.4267.0343910425.9267.7394610445.7169.0815810478.4269.7498310539.2472.64012
#Mann= 3 , 0 , 0
 9630.32    0.12       0 9630.32    0.12       010539.24    0.12       0
#XS Ineff= 2 , 0
       09953.407                       0
Bank Sta=9630.32,10539.24
Exp/Cntr=0.3,0.1

Type RM Length L Ch R = 1 ,3816.949,240.724200,240.724200,240.724200
XS GIS Cut Line= 6
1249236.76403595846600.4480679611249233.99462795846357.107038807
1249230.90955505846169.0457607581249226.45364961846102.591048538
1249212.50801492845946.5270509561248879.12514706845669.892512404
#Sta/Elev= 30
9518.52793.902039538.73489.645699568.26384.94852 9587.9580.783079607.63680.85424
9637.16575.48003  9683.1 70.34099692.94369.819349702.786 68.1404 9715.9167.52637
9729.03566.035229742.159  65.7269791.37758.538449807.783 56.76189863.56553.28518
9886.53452.540049899.65951.279999985.05750.875539998.21450.2714310031.1152.31426
10120.0455.5045510166.1655.8274210223.8457.0619810383.1161.5930710418.1763.75583
10443.75 63.660710503.4465.1077910546.0767.1474610568.0766.8913310606.4767.62764
#Mann= 3 , 0 , 0
9518.527    0.12       09518.527    0.12       010606.47    0.12       0
#XS Ineff= 2 , 0
       0                               0
Bank Sta=9518.527,10606.47
Exp/Cntr=0.3,0.1

Type RM Length L Ch R = 1 ,3576.225,328.338500,328.338500,328.338500
XS GIS Cut Line= 3
1249436.96340768846521.6282577921249440.28813615 845997.61355467
1249140.40986929 845756.69806796
#Sta/Elev= 30
9688.20591.917249711.612 85.16329721.45584.294179744.42180.713219770.66873.11338
9790.354  69.0599836.28657.51221 9849.4154.989129869.09553.143169892.06249.54532
9924.87147.04251 9957.6846.00984 9997.0545.6723610049.5445.8342810082.3546.78268
10095.4847.8243710115.1647.7084910134.8549.1122310151.2548.8849210236.9551.06214
10270.6251.3141910291.6652.5238610308.4952.6417710319.1753.6397210333.7553.14378
10354.7953.5995710387.2755.6064910485.2557.0250110531.5459.06501 10596.960.45043
#Mann= 3 , 0 , 0
9688.205    0.12       09688.205    0.12       0 10596.9    0.12       0
#XS Ineff= 2 , 0
       0                               0
Bank Sta=9688.205,10596.9
Exp/Cntr=0.3,0.1

Type RM Length L Ch R = 1 ,3247.886,184.995300,184.995300,184.995300
XS GIS Cut Line= 4
1249618.50693637846541.1358524561249768.24651971846204.764324695
1249666.24999192845842.3511302321249555.57290861845449.555991352
#Sta/Elev= 30
9563.09384.893059570.56481.618599609.92268.568129624.43266.485799642.38961.13123
9671.11856.478529714.213 51.58089811.176 44.08589926.09647.118869943.40249.43572
9987.70940.2472310001.3439.2269810032.0240.39096 10066.143.8602410093.3745.32091
10103.5944.8731510141.0846.2561310195.6245.9506210294.4648.2536810342.1747.65813
10383.0841.4269210389.8943.4679810403.5344.8779710427.3945.1224410485.3450.15437
10539.8752.7226710567.1452.7834910625.0955.2901510693.2655.2626510715.8756.36713
#Mann= 3 , 0 , 0
9563.093    0.12       09563.093    0.12       010715.87    0.12       0
#XS Ineff= 2 , 0
       0                10130.94       0
Bank Sta=9563.093,10715.87
Exp/Cntr=0.3,0.1

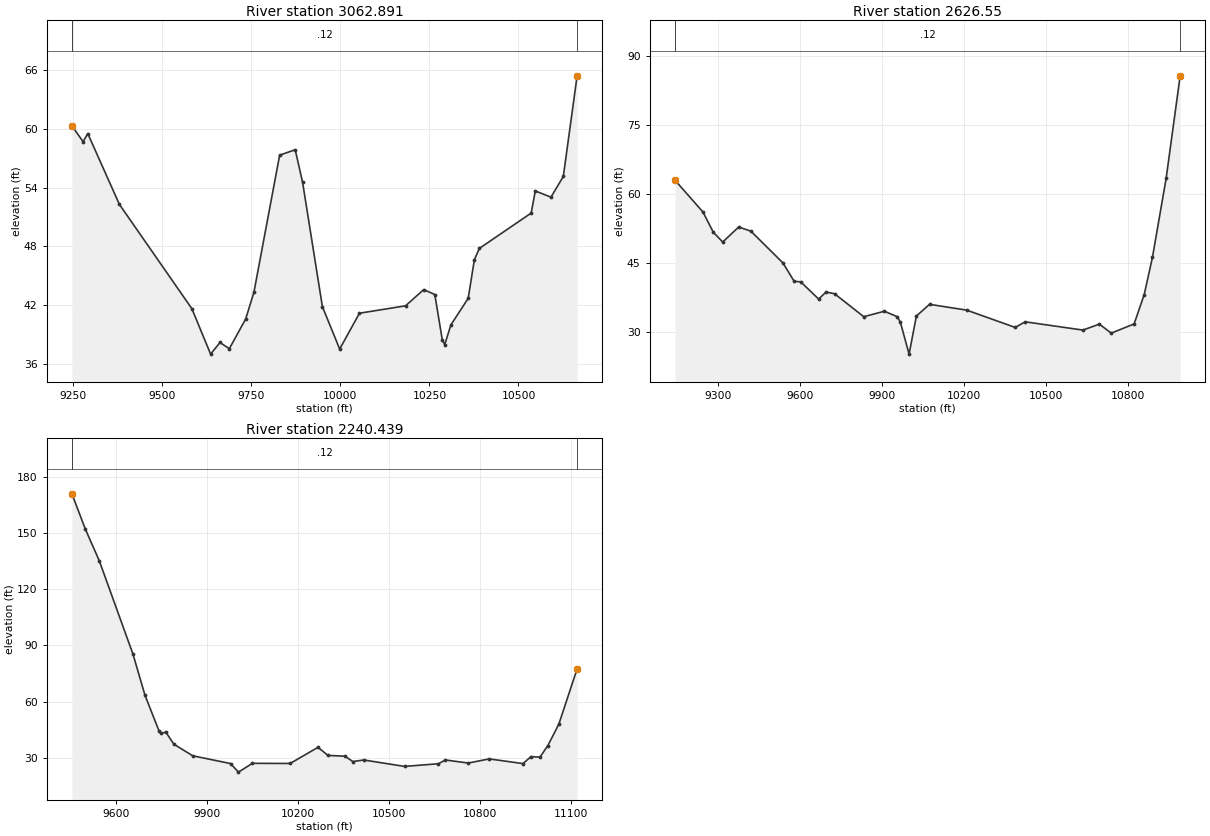
Type RM Length L Ch R = 1 ,3062.891,436.340800,436.340800,436.340800
XS GIS Cut Line= 3
1249909.30554751846769.0004357991249937.51735303846161.361546904
1249674.93054751845395.302519143
#Sta/Elev= 30
9246.49360.319329277.80558.695719290.94259.53302 9379.6252.299759583.25141.62857
9635.80136.990019662.07638.178939688.35137.545069734.332 40.59159757.32243.30034
9829.57857.322689873.25457.878869894.06354.532579949.55541.84278 9998.1137.50701
 10053.641.1718610182.9141.9257910233.9543.5829910265.16 43.080110285.9738.47443
10292.9137.9505610310.2539.9782610358.8142.6882710376.1546.6255410390.0247.78999
10535.6851.4073410547.1653.6648610591.1853.0328410625.8655.14814 10664.665.43026
#Mann= 3 , 0 , 0
9246.493    0.12       09246.493    0.12       0 10664.6    0.12       0
#XS Ineff= 2 , 0
       0                10069.13       0
Bank Sta=9246.493,10664.6
Exp/Cntr=0.3,0.1

Type RM Length L Ch R = 1 , 2626.55,386.110900,386.110900,386.110900
XS GIS Cut Line= 3
1250017.81249195846933.930991367 1250322.1438849845975.712554917
1250493.58485714845148.846235484
#Sta/Elev= 30
 9141.7262.922469244.31756.006769282.18251.603049316.60649.490569375.12552.75193
9419.87651.843979536.91544.955959578.22340.953619602.31940.833689667.72337.10751
9695.26238.625469726.243 38.24939832.95533.266929908.686 34.45559955.65233.26404
9967.206 32.05429999.00625.1361810025.73 33.405410073.9235.9532310209.89 34.6927
10387.4730.9384310424.3332.1502710635.4230.3606910695.7331.6515110739.2929.69992
10823.0531.6978210859.9138.0687710890.0746.1378910940.3363.3347510991.5685.58774
#Mann= 3 , 0 , 0
 9141.72    0.12       0 9141.72    0.12       010991.56    0.12       0
#XS Ineff= 2 , 0
       09945.762        10082.21       0
Bank Sta=9141.72,10991.56
Exp/Cntr=0.3,0.1

Type RM Length L Ch R = 1 ,2240.439,0.000000,0.000000,0.000000
XS GIS Cut Line= 5
1250620.81569206846827.9994002061250617.99990502 846620.86179186
1250616.85782084846201.161927171 1250615.0900448846117.303216704
1250570.88520432845161.686223905
#Sta/Elev= 30
9453.322171.10779497.671152.19719543.607135.30589655.16685.170759694.53663.29971
9740.46844.41253 9747.0342.945399763.43443.629319789.68137.177759852.01730.98321
9976.68926.8307410002.94 22.235910048.8726.9420710173.5726.8684210265.5335.50497
10298.3731.1642410354.2130.7687310380.4827.8905510416.6128.7341310551.2725.28629
10662.9326.7223410685.9328.7328310761.4727.0936810830.4429.30235 10942.126.80927
10968.3830.5198510997.9430.2486211024.21 36.452611060.3447.90674 11120.777.48444
#Mann= 3 , 0 , 0
9453.322    0.12       09453.322    0.12       0 11120.7    0.12       0
#XS Ineff= 2 , 0
       09910.885        10099.74       0
Bank Sta=9453.322,11120.7
Exp/Cntr=0.3,0.1